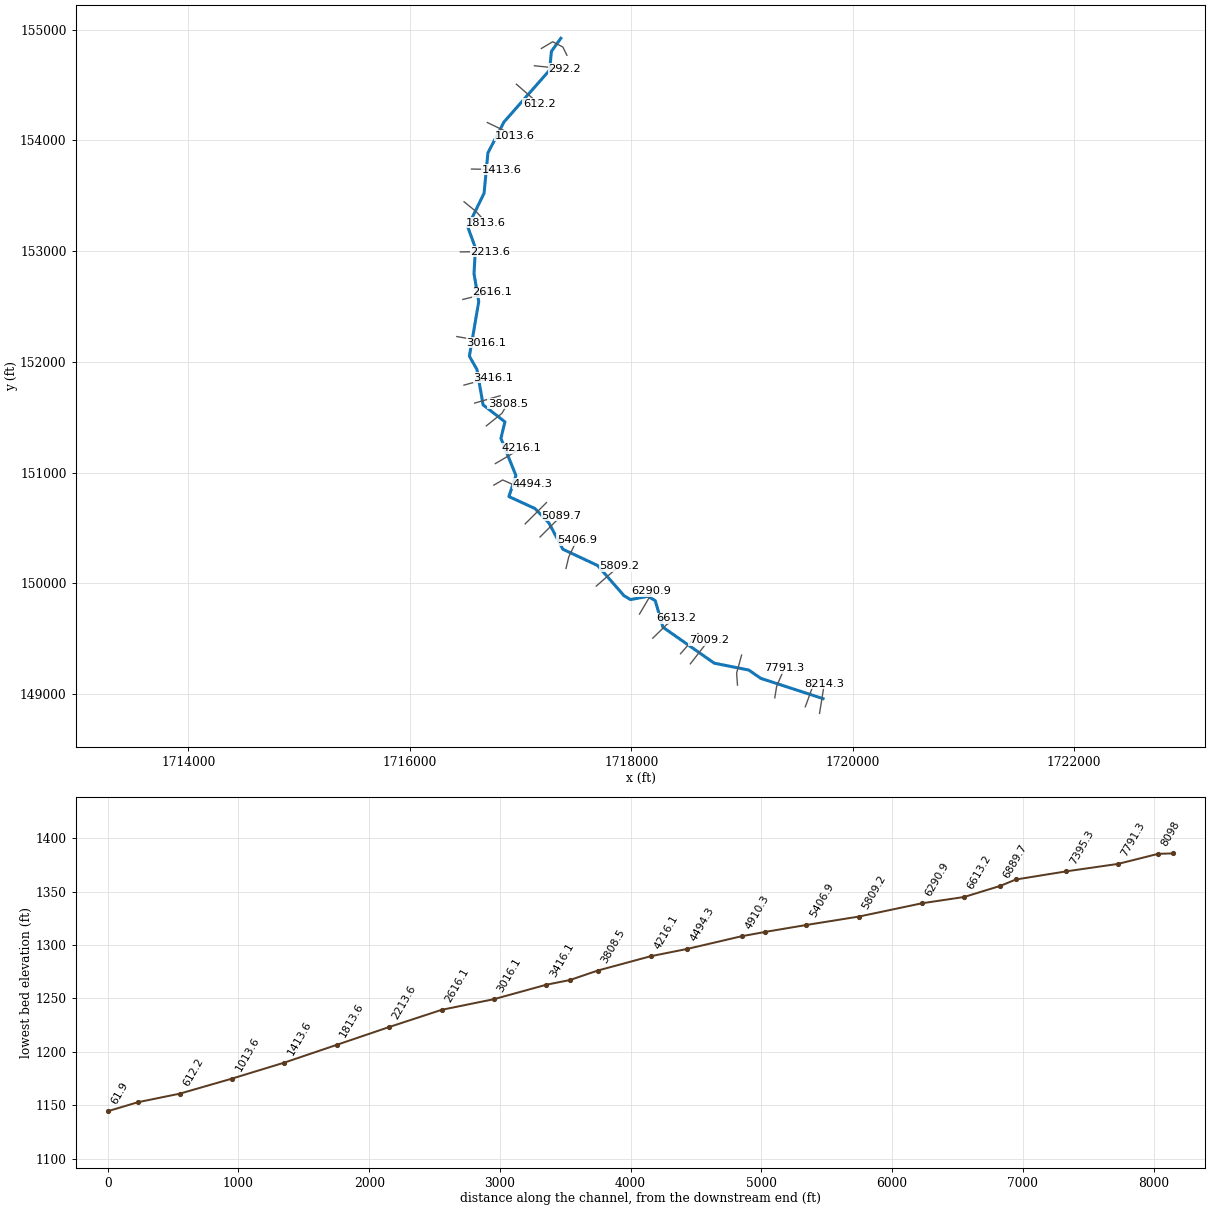
--- Hurricane Branch A.prj (project) ---

Proj Title=Hurricane Branch A
Current Plan=p01
Default Exp/Contr=0,0
English Units
Geom File=g01
Flow File=f01
Plan File=p01
BEGIN DESCRIPTION:
END DESCRIPTION:
DSS Export Rating Curves= 0
DSS Export Rating Curve Sorted= 0
DSS Export Volume Flow Curves= 0
DXF OffsetX= 0
DXF OffsetY= 0
DXF ScaleX= 0
DXF ScaleY= 0

--- Hurricane Branch A.p01 (plan) ---

Plan Title=Floodplain
Program Version=4.00
Geom File=g01
Flow File=f01
K Sum by GR=0
Std Step Tol=0.01
Critical Tol=0.01
Num of Std Step Trials=20
Max Error Tol=0.3
Flow Tol Ratio=0.001
Split Flow NTrial=30
Split Flow Tol=0.02
Split Flow Ratio=0.02
Log Output Level=0
Friction Slope Method=1
Unsteady Friction Slope Method=2
Unsteady Bridges Friction Slope Method=1
Global Log Level=0
CheckData=False
Run HTab=0
Run UNet=0
Run PostProcess=0
UNET Theta=0
UNET Theta Warmup=0
UNET ZTol=0
UNET ZSATol=0
UNET MxIter=0
UNET MaxInSteps=0
UNET DtIC=0
UNET DtMin=0
UNET MaxCRTS=0
UNET WFStab=0
UNET SFStab=0
UNET WFX=0
UNET SFX=0
UNET DSS MLevel=0
UNET DZMax Abort=0
UNET Convert EG Bridges=0
UNET Use Existing IB Tables=0
UNET Froude Limit=0
UNET Froude Power=0
Write IC File=0
Echo Input=False
Echo Output=False
Write Detailed=0

--- Hurricane Branch A.f01 (steady flow) ---

Flow Title=NFF Regression Equation
Program Version=4.00
Number of Profiles=1
Profile Names=P100yr
River Rch & RM=Hurricane Bra...,Main      ,8214.3
539.2173
River Rch & RM=Hurricane Bra...,Main      ,8098
540.5893
River Rch & RM=Hurricane Bra...,Main      ,7791.3
646.5268
River Rch & RM=Hurricane Bra...,Main      ,7009.2
661.1529
River Rch & RM=Hurricane Bra...,Main      ,6290.9
732.6419
River Rch & RM=Hurricane Bra...,Main      ,5089.7
808.1282
River Rch & RM=Hurricane Bra...,Main      ,3808.5
889.7660
River Rch & RM=Hurricane Bra...,Main      ,292.2
981.4448
Boundary for River Rch & Prof#=Hurricane Bra...,Main      ,1
Up Type=0
Dn Type=3
Dn Slope=0.032522

--- Hurricane Branch A.g01 (geometry) ---

Geom Title=Geometry
Program Version=4.00

River Reach=Hurricane Bra...,Main
Reach XY= 30
     1719731.926      148958.481     1719170.238      149141.393
     1719060.902      149216.558     1718749.441        149278.5
     1718286.311       149603.26      1718216.81      149842.722
     1718152.363      149882.527     1717993.143      149852.832
     1717934.383      149888.214     1717696.183      150160.532
     1717382.165      150307.748     1717256.431      150544.683
     1717130.065      150675.472      1716895.07      150783.327
     1716958.294      150973.498     1716822.997      151309.195
     1716859.011      151458.307     1716661.881      151611.841
      1716606.28      151930.914     1716538.196      152050.805
     1716622.707      152543.787     1716579.884      152795.846
     1716593.012      153027.136     1716522.878      153219.843
     1716670.726      153522.489     1716705.477      153887.054
     1716849.856      154165.033     1717262.118      154633.875
     1717279.177      154804.468     1717363.711      154921.541

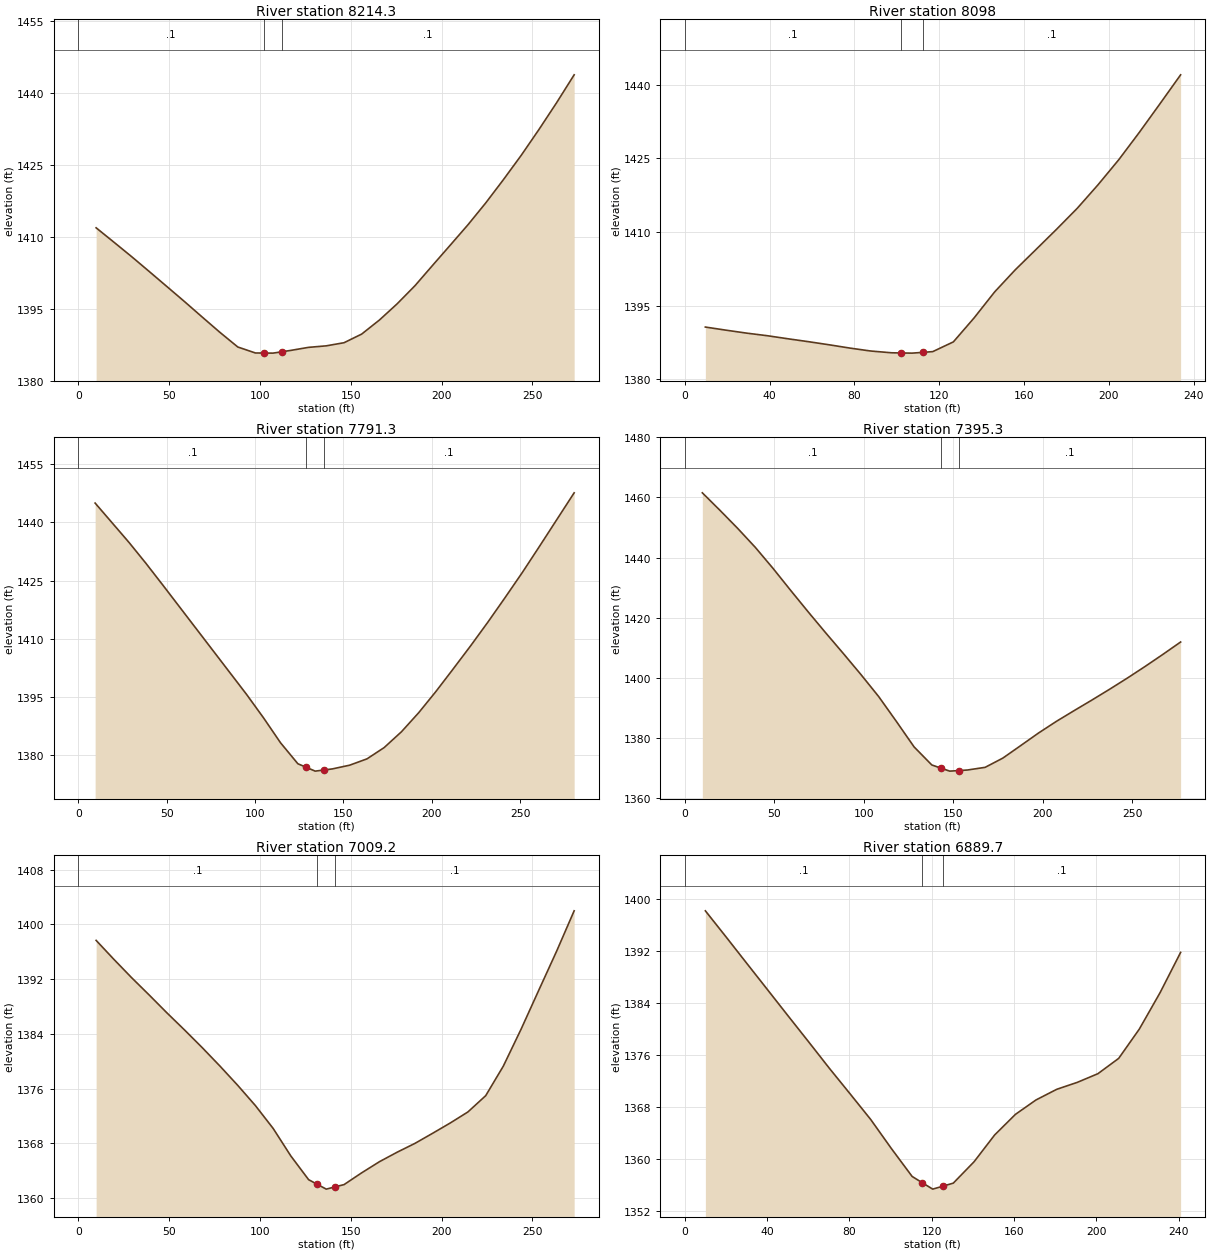
Type RM Length L Ch R = 1 ,8214.3  ,120,116.3,112.5
XS GIS Cut Line= 3
     1719700.366      148825.303     1719722.053      148960.069
      1719743.74      149094.836
#Sta/Elev= 30
     9.8 1411.86    19.5 1408.89    29.3 1405.86      39 1402.76    48.7 1399.63
    58.5 1396.46    68.2 1393.25      78 1390.04    87.8    1387    97.5 1385.75
   102.2 1385.74   107.2 1385.72   112.2 1386.01     117 1386.29   126.7 1386.92
   136.5 1387.24   146.3 1387.89     156 1389.69   165.8 1392.63   175.5 1395.99
   185.3 1399.76     195    1404   204.8 1408.25   214.5 1412.48   224.3 1417.04
     234 1421.88   243.8 1426.95   253.5  1432.3   263.3 1437.93     273 1443.77
#Mann= 3 , 0 , 0
       0      .1       0   102.2    .045       0   112.2      .1       0
Bank Sta=102.2,112.2
XS Rating Curve= 0 ,0
Exp/Cntr=0.3,0.1

Type RM Length L Ch R = 1 ,8098    ,307.8,306.7,305.6
XS GIS Cut Line= 2
      1719572.03      148884.787     1719651.681      149104.721
#Sta/Elev= 26
     9.7 1390.65    19.5 1390.01    29.2 1389.41      39 1388.88    48.7 1388.26
    58.5 1387.66    68.2 1387.03      78 1386.36    87.7 1385.77    97.5 1385.41
   102.2 1385.37   107.2 1385.34   112.2 1385.49     117 1385.65   126.7 1387.63
   136.4 1392.47   146.2 1397.82   155.9 1402.31   165.7 1406.45   175.4 1410.57
   185.2 1414.86   194.9  1419.6   204.7 1424.71   214.4 1430.28   224.2 1436.14
   233.9 1442.01
#Mann= 3 , 0 , 0
       0      .1       0   102.2    .045       0   112.2      .1       0
Bank Sta=102.2,112.2
XS Rating Curve= 0 ,0
Exp/Cntr=0.3,0.1

Type RM Length L Ch R = 1 ,7791.3  ,393.2,396,398.6
XS GIS Cut Line= 3
     1719296.144      148965.716     1719312.864      149069.056
     1719381.816      149230.738
#Sta/Elev= 25
     9.5 1444.97    28.6 1434.87    38.1 1429.53    47.6 1423.96    95.2 1395.66
   104.7 1389.68   114.4 1383.21   124.2 1377.81     129 1376.88     134 1375.91
     139  1376.2   143.7 1376.48   153.5 1377.44   163.3 1379.07     173 1381.97
   182.8 1386.05   192.6 1390.98   202.3 1396.43   212.1 1402.26   221.9 1408.17
   231.6 1414.24   241.4  1420.6   251.2  1427.1   260.9 1433.83   280.5 1447.61
#Mann= 3 , 0 , 0
       0      .1       0     129    .045       0     139      .1       0
Bank Sta=129,139
XS Rating Curve= 0 ,0
Exp/Cntr=0.3,0.1

Type RM Length L Ch R = 1 ,7395.3  ,393.9,386.1,378.3
XS GIS Cut Line= 3
      1718959.46      149081.174     1718951.458      149189.129
     1718996.421       149351.78
#Sta/Elev= 30
     9.8 1461.53    19.7 1455.68    29.5 1449.73    39.4 1443.38    49.2 1436.46
      59 1429.18    68.9 1421.95    78.7 1414.96    88.6 1408.05    98.4 1401.08
   108.3 1393.76   118.2 1385.48   128.1    1377     138 1370.99     143 1369.96
     148 1368.94     153 1369.12   157.9 1369.31   167.8  1370.2   177.7 1373.28
   187.7 1377.45   197.6 1381.61   207.5 1385.46   217.4 1389.03   227.4 1392.57
   237.3 1396.17   247.2 1399.88   257.1 1403.74   267.1 1407.78     277  1411.9
#Mann= 3 , 0 , 0
       0      .1       0     143    .045       0     153      .1       0
Bank Sta=143,153
XS Rating Curve= 0 ,0
Exp/Cntr=0.3,0.1

Type RM Length L Ch R = 1 ,7009.2  ,120.5,119.5,118.3
XS GIS Cut Line= 3
     1718533.521      149272.725     1718617.458       149380.37
     1718700.853      149488.432
#Sta/Elev= 30
     9.8 1397.66    19.5 1394.91    29.3 1392.22      39 1389.68    48.8 1387.06
    58.5 1384.56    68.3 1381.96      78 1379.28    87.8 1376.46    97.5 1373.51
   107.3 1370.16     117 1366.15   126.8 1362.68   131.5 1362.01   136.5  1361.3
   141.5 1361.64   146.3 1361.96     156 1363.68   165.8 1365.31   175.5 1366.69
   185.3 1367.98     195 1369.45   204.8 1370.97   214.5 1372.58   224.3 1374.96
     234 1379.28   243.8 1384.69   253.5 1390.36   263.3 1396.05     273 1401.98
#Mann= 3 , 0 , 0
       0      .1       0   131.5    .045       0   141.5      .1       0
Bank Sta=131.5,141.5
XS Rating Curve= 0 ,0
Exp/Cntr=0.3,0.1

Type RM Length L Ch R = 1 ,6889.7  ,278.1,276.5,274.9
XS GIS Cut Line= 2
     1718445.014      149363.887     1718603.129      149545.779
#Sta/Elev= 26
      10 1398.14    20.1 1394.11    30.1 1390.07    40.2 1386.01    50.2 1381.98
    60.3 1377.94    70.3  1373.9    80.3    1370    90.4 1366.02   100.4 1361.57
   110.5 1357.27   115.5 1356.29   120.5 1355.32   125.5 1355.78   130.5 1356.24
   140.6 1359.53   150.6 1363.65   160.7 1366.82   170.7 1369.04   180.8 1370.68
   190.8 1371.75   200.8 1373.08   210.9 1375.44   220.9 1379.93     231 1385.54
     241 1391.74
#Mann= 3 , 0 , 0
       0      .1       0   115.5    .045       0   125.5      .1       0
Bank Sta=115.5,125.5
XS Rating Curve= 0 ,0
Exp/Cntr=0.3,0.1

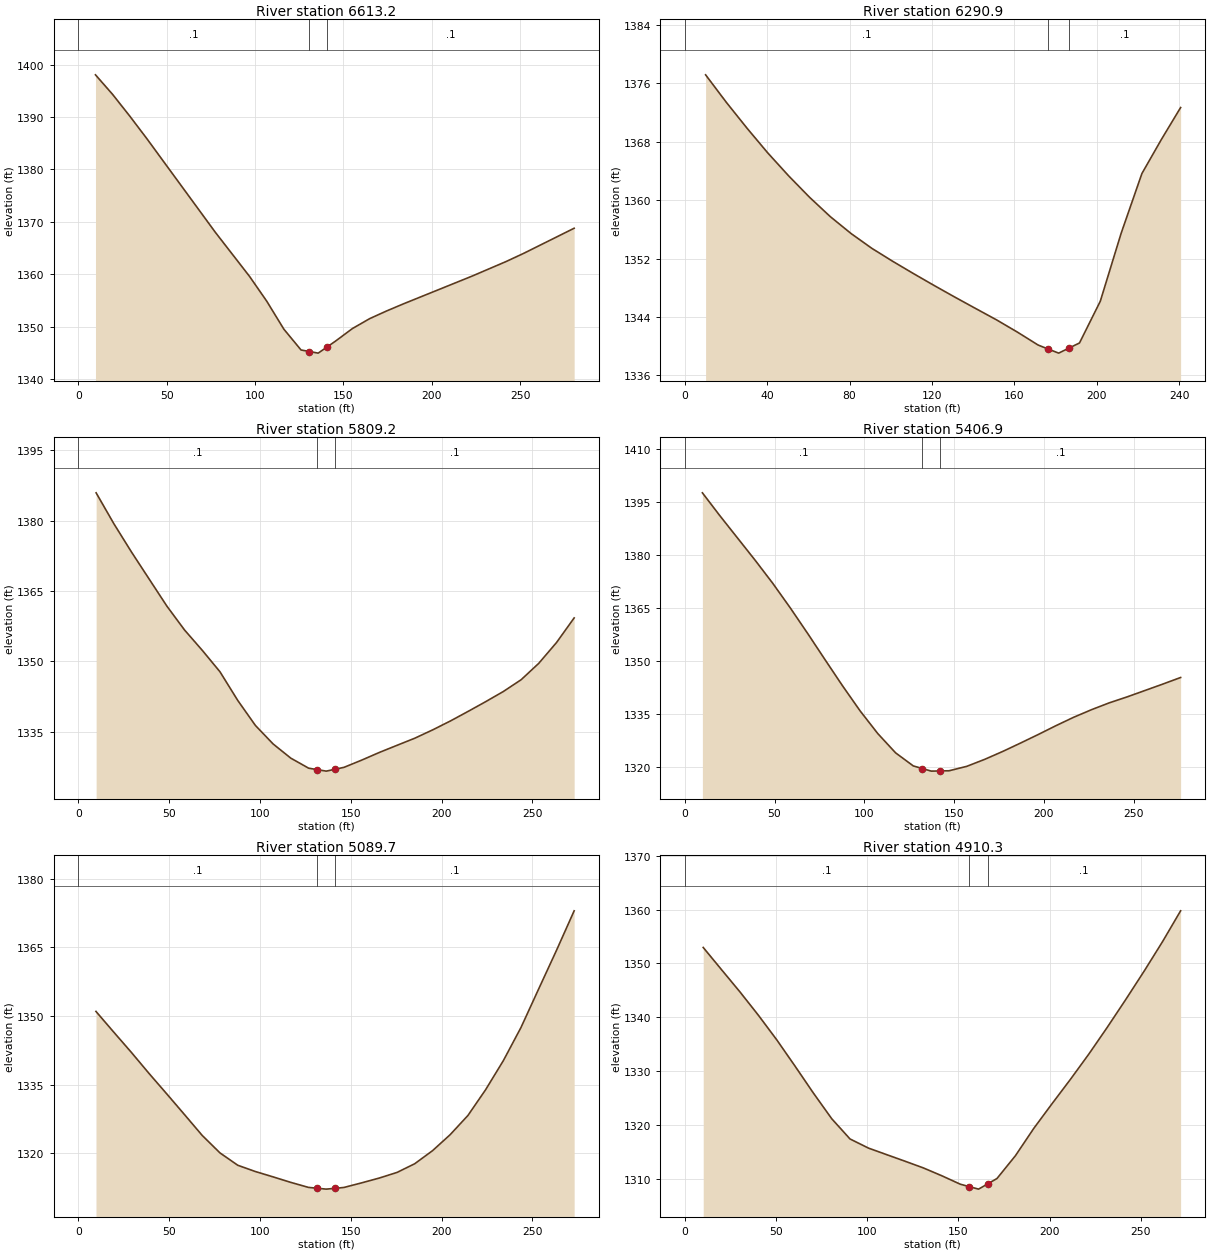
Type RM Length L Ch R = 1 ,6613.2  ,317.1,322.3,327.4
XS GIS Cut Line= 3
     1718194.469      149504.452     1718318.998       149626.62
     1718408.746       149683.09
#Sta/Elev= 21
     9.7 1398.05    19.4 1394.31    29.1 1390.17    38.8 1385.85    77.5 1367.99
    96.9 1359.55   106.6 1354.83   116.3 1349.48     126 1345.52   130.7 1345.23
   135.7 1344.92   140.7 1346.09   145.4 1347.19   155.1 1349.62   164.8  1351.5
   174.4 1352.97   184.1 1354.35   222.6  1359.6   241.9 1362.39   251.6 1363.91
   280.5 1368.76
#Mann= 3 , 0 , 0
       0      .1       0   130.7    .045       0   140.7      .1       0
Bank Sta=130.7,140.7
XS Rating Curve= 0 ,0
Exp/Cntr=0.3,0.1

Type RM Length L Ch R = 1 ,6290.9  ,488.3,481.7,474.9
XS GIS Cut Line= 3
      1718074.28      149722.033     1718187.037      149913.129
     1718181.093      149930.961
#Sta/Elev= 26
    10.1 1377.16    20.2 1373.38    30.3 1369.82    40.3 1366.46    50.4 1363.33
    60.5 1360.41    70.6 1357.75    80.7 1355.43    90.8  1353.4   100.9 1351.63
   110.9 1349.96     121 1348.32   131.1 1346.72   141.2 1345.16   151.3 1343.61
   161.4 1341.94   171.5 1340.16   176.5  1339.6   181.5 1339.05   186.5 1339.74
   191.6 1340.44   201.7 1346.15   211.8 1355.44   221.9 1363.64   231.3 1368.28
   240.7 1372.68
#Mann= 3 , 0 , 0
       0      .1       0   176.5    .045       0   186.5      .1       0
Bank Sta=176.5,186.5
XS Rating Curve= 0 ,0
Exp/Cntr=0.3,0.1

Type RM Length L Ch R = 1 ,5809.2  ,394.2,402.3,410.6
XS GIS Cut Line= 3
      1717683.93      149974.759     1717786.622      150064.732
      1717890.12      150153.717
#Sta/Elev= 30
     9.8  1385.9    19.5 1379.36    29.3 1373.27      39 1367.53    48.8 1361.74
    58.5 1356.67    68.3 1352.32      78 1347.77    87.8 1341.66    97.5 1336.34
   107.3 1332.38     117 1329.37   126.8 1327.24   131.5 1326.93   136.5 1326.61
   141.5 1327.02   146.3 1327.42     156 1328.95   165.8  1330.6   175.5 1332.11
   185.3 1333.63     195 1335.38   204.8 1337.28   214.5 1339.31   224.3 1341.41
     234 1343.57   243.8 1346.08   253.5 1349.57   263.3 1354.01     273 1359.25
#Mann= 3 , 0 , 0
       0      .1       0   131.5    .045       0   141.5      .1       0
Bank Sta=131.5,141.5
XS Rating Curve= 0 ,0
Exp/Cntr=0.3,0.1

Type RM Length L Ch R = 1 ,5406.9  ,324.1,317.2,310.3
XS GIS Cut Line= 3
     1717410.603      150134.335     1717435.694      150238.869
     1717508.561       150390.98
#Sta/Elev= 30
     9.8 1397.58    19.5 1391.12    29.3 1384.83    39.1 1378.54    48.9 1372.02
    58.6  1365.1    68.4 1357.78    78.2 1350.26      88 1342.82    97.7 1335.79
   107.5 1329.39   117.4 1323.94   127.3 1320.22   132.3 1319.49   137.3 1318.75
   142.3  1318.8   147.2 1318.85   157.1 1320.11     167 1322.07     177  1324.3
   186.9 1326.67   196.8  1329.1   206.7 1331.61   216.6    1334   226.6 1336.16
   236.5  1338.1   246.4 1339.78   256.3 1341.58   266.2 1343.39   276.2 1345.27
#Mann= 3 , 0 , 0
       0      .1       0   132.3    .045       0   142.3      .1       0
Bank Sta=132.3,142.3
XS Rating Curve= 0 ,0
Exp/Cntr=0.3,0.1

Type RM Length L Ch R = 1 ,5089.7  ,179.4,179.3,179.3
XS GIS Cut Line= 3
     1717176.479      150418.518     1717272.999      150515.038
      1717369.52      150611.558
#Sta/Elev= 30
     9.7 1350.99    19.5 1346.47    29.3    1342      39 1337.41    48.8 1332.93
    58.5 1328.44    68.2 1323.91      78 1320.09    87.8 1317.39    97.5 1316.02
   107.2 1314.86     117 1313.65   126.7 1312.56   131.5 1312.37   136.5 1312.18
   141.5 1312.36   146.2 1312.54     156 1313.55   165.7  1314.6   175.5 1315.83
   185.2 1317.72     195 1320.57   204.7 1324.06   214.5 1328.26   224.2 1333.86
     234 1340.23   243.7 1347.46   253.5 1355.93   263.3 1364.35     273 1372.96
#Mann= 3 , 0 , 0
       0      .1       0   131.5    .045       0   141.5      .1       0
Bank Sta=131.5,141.5
XS Rating Curve= 0 ,0
Exp/Cntr=0.3,0.1

Type RM Length L Ch R = 1 ,4910.3  ,441.1,416,390.9
XS GIS Cut Line= 2
     1717042.118      150536.753     1717234.402      150729.037
#Sta/Elev= 29
    10.1 1352.97    20.1 1348.87    30.2 1344.75    40.3 1340.43    50.4 1335.86
    60.4    1331    70.5 1325.99    80.6 1321.21    90.6 1317.47   100.7 1315.78
   110.8 1314.55   120.9 1313.33   130.9 1312.09     141 1310.64   151.1 1309.08
   156.1 1308.62   161.1 1308.17   166.1 1309.14   171.2 1310.14   181.3 1314.36
   191.4 1319.44   201.4 1324.01   211.5 1328.53   221.6 1333.22   231.6 1338.13
   241.7 1343.26   251.8 1348.53   261.9    1354   271.9 1359.76
#Mann= 3 , 0 , 0
       0      .1       0   156.1    .045       0   166.1      .1       0
Bank Sta=156.1,166.1
XS Rating Curve= 0 ,0
Exp/Cntr=0.3,0.1

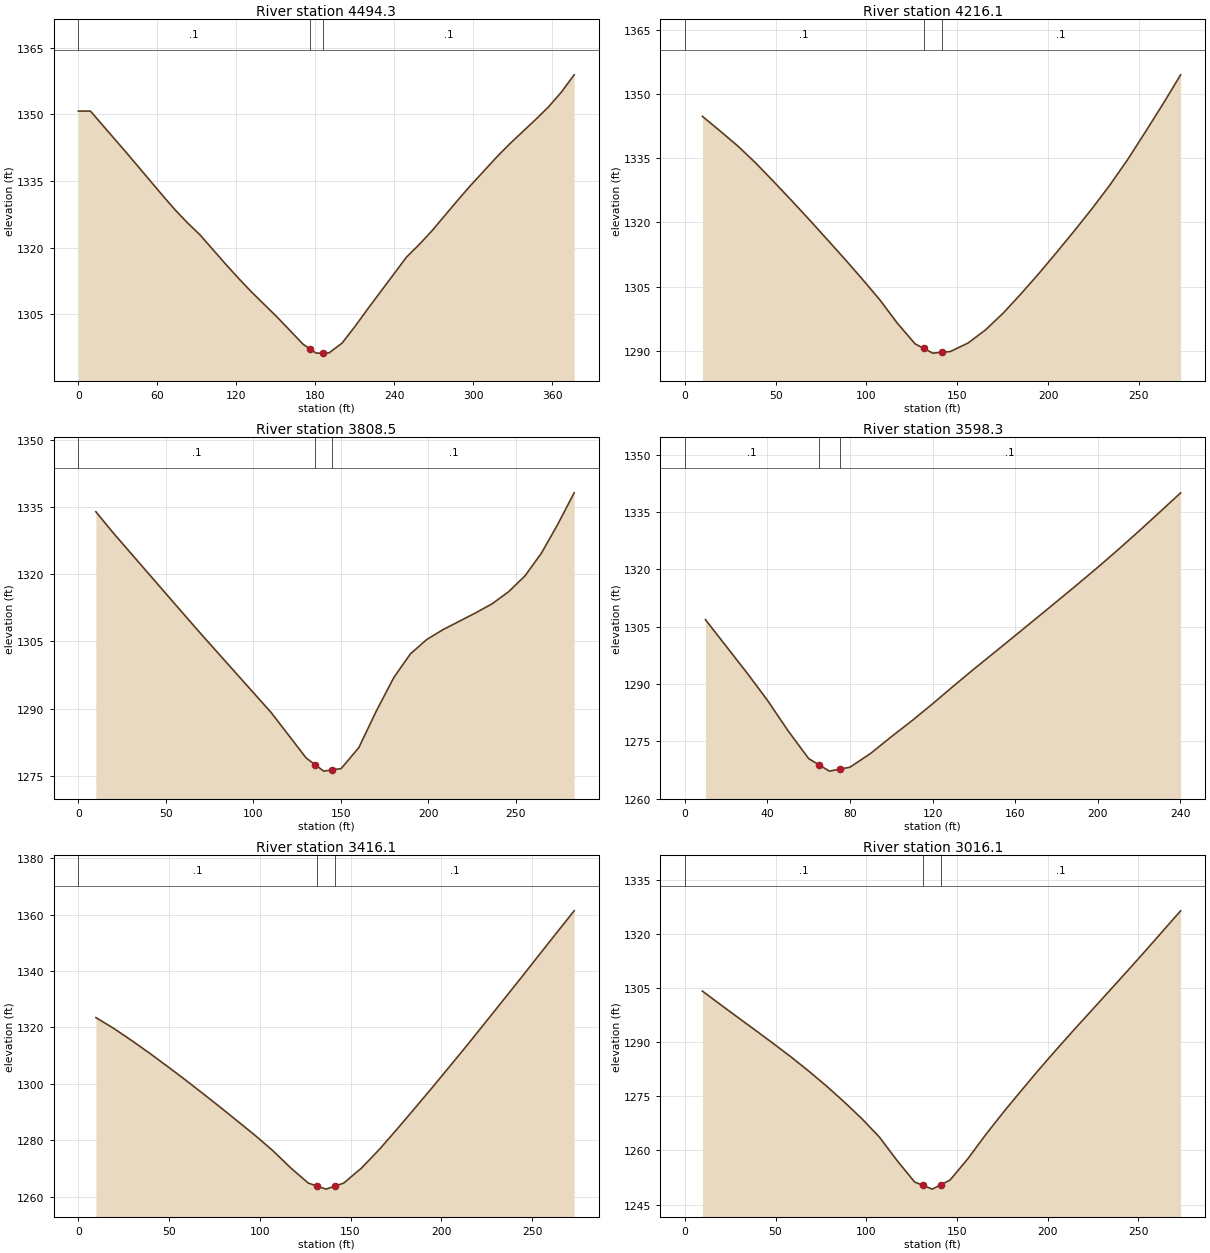
Type RM Length L Ch R = 1 ,4494.3  ,259,278.2,297.4
XS GIS Cut Line= 4
     1716759.247      150886.784     1716838.944      150933.298
     1716982.043      150868.585     1717105.298      150900.504
#Sta/Elev= 30
       0 1350.75     9.2 1350.75    36.9 1341.27    64.6 1331.56    73.8 1328.43
    83.1 1325.56    92.3 1322.94   111.9 1316.32   121.7 1313.12   131.5 1310.07
   151.2 1304.34   170.8 1298.27   175.6  1297.3   180.6 1296.29   185.6 1296.31
   190.4 1296.34   200.3 1298.54   210.1 1302.28   219.9 1306.27   249.3 1317.91
   259.1 1320.78   268.9 1323.92   288.5 1330.81   298.3 1334.13   317.9 1340.45
   327.7 1343.39   347.3 1348.84   357.1 1351.69   366.9 1355.02   376.6 1358.91
#Mann= 3 , 0 , 0
       0      .1       0   175.6    .045       0   185.6      .1       0
Bank Sta=175.6,185.6
XS Rating Curve= 0 ,0
Exp/Cntr=0.3,0.1

Type RM Length L Ch R = 1 ,4216.1  ,404.5,407.6,410.7
XS GIS Cut Line= 3
     1716772.448      151081.025     1716890.206      151150.056
     1717007.965      151219.086
#Sta/Elev= 30
     9.7 1344.78    19.5 1341.34    29.2 1337.85      39 1333.91    48.7 1329.65
    58.5 1325.26    68.3 1320.77      78 1316.23    87.8  1311.6    97.5  1306.9
   107.3 1301.99     117 1296.51   126.8 1291.66   131.5 1290.61   136.5  1289.5
   141.5 1289.69   146.2 1289.87     156 1291.87   165.7 1294.96   175.5 1298.93
   185.2 1303.39     195 1308.11   204.7 1313.01   214.5 1318.06   224.3 1323.28
     234 1328.71   243.8 1334.66   253.5 1341.07   263.3 1347.67     273 1354.47
#Mann= 3 , 0 , 0
       0      .1       0   131.5    .045       0   141.5      .1       0
Bank Sta=131.5,141.5
XS Rating Curve= 0 ,0
Exp/Cntr=0.3,0.1

Type RM Length L Ch R = 1 ,3808.5  ,218.2,210.2,202.3
XS GIS Cut Line= 3
      1716691.17      151421.828     1716831.766      151534.699
     1716884.149      151623.372
#Sta/Elev= 23
      10    1334      20 1329.24    60.1 1311.15    70.1 1306.67   110.2 1289.09
   130.2 1278.93   135.2 1277.46   140.2    1276   145.2 1276.29   150.2 1276.58
   160.3 1281.28   170.3 1289.47   180.3 1296.95   189.7  1302.2     199  1305.4
   208.4 1307.64   227.1  1311.4   236.5 1313.43   245.8 1316.09   255.2 1319.65
   264.6 1324.74   273.9 1331.16   283.3 1338.22
#Mann= 3 , 0 , 0
       0      .1       0   135.2    .045       0   145.2      .1       0
Bank Sta=135.2,145.2
XS Rating Curve= 0 ,0
Exp/Cntr=0.3,0.1

Type RM Length L Ch R = 1 ,3598.3  ,182.4,182.1,180.9
XS GIS Cut Line= 2
     1716585.677      151627.428     1716816.311      151694.003
#Sta/Elev= 26
      10 1306.85      20 1299.93      30 1293.01      40 1285.77      50 1277.78
      60 1270.48      65 1268.85      70 1267.21      75 1267.73      80 1268.24
      90 1271.85     100 1276.21     110  1280.4     120 1284.83     130 1289.43
     140 1293.92     150  1298.3     160 1302.69     170 1307.12     180 1311.55
     190 1316.02     200 1320.56     210 1325.25     220 1330.07     230 1335.01
   240.1 1340.05
#Mann= 3 , 0 , 0
       0      .1       0      65    .045       0      75      .1       0
Bank Sta=65,75
XS Rating Curve= 0 ,0
Exp/Cntr=0.3,0.1

Type RM Length L Ch R = 1 ,3416.1  ,409.2,400,390.9
XS GIS Cut Line= 3
       1716489.5      151789.752     1716621.049      151826.041
     1716754.508      151855.686
#Sta/Elev= 30
     9.7  1323.5    19.5 1319.69    29.2 1315.47      39 1311.02    48.7 1306.42
    58.5 1301.68    68.2 1296.83      78 1291.88    87.7 1286.84    97.5 1281.74
   107.2 1276.38     117 1270.29   126.7  1264.9   131.5 1263.85   136.5 1262.76
   141.5 1263.85   146.2 1264.89     156 1270.21   165.8 1276.78   175.5 1283.91
   185.3 1291.33   195.1  1298.8   204.8 1306.36   214.6 1314.02   224.3 1321.79
   234.1 1329.65   243.9 1337.54   253.6 1345.46   263.4 1353.41   273.2 1361.31
#Mann= 3 , 0 , 0
       0      .1       0   131.5    .045       0   141.5      .1       0
Bank Sta=131.5,141.5
XS Rating Curve= 0 ,0
Exp/Cntr=0.3,0.1

Type RM Length L Ch R = 1 ,3016.1  ,391.6,400,409.4
XS GIS Cut Line= 3
     1716425.001      152228.358     1716559.286      152204.268
     1716692.686      152173.619
#Sta/Elev= 30
     9.7 1304.13    19.5 1300.46    29.2 1296.86      39 1293.26    48.7 1289.64
    58.5 1285.92    68.2 1282.02      78 1277.88    87.7  1273.5    97.4 1268.89
   107.2 1263.73   116.9 1257.26   126.7 1251.24   131.4 1250.29   136.4 1249.27
   141.4 1250.55   146.2 1251.77     156 1257.67   165.8 1264.32   175.5  1270.5
   185.3 1276.46   195.1 1282.32   204.9 1287.98   214.6 1293.45   224.4 1298.86
   234.2 1304.28     244 1309.73   253.8 1315.23   263.5 1320.78   273.3 1326.37
#Mann= 3 , 0 , 0
       0      .1       0   131.4    .045       0   141.4      .1       0
Bank Sta=131.4,141.4
XS Rating Curve= 0 ,0
Exp/Cntr=0.3,0.1

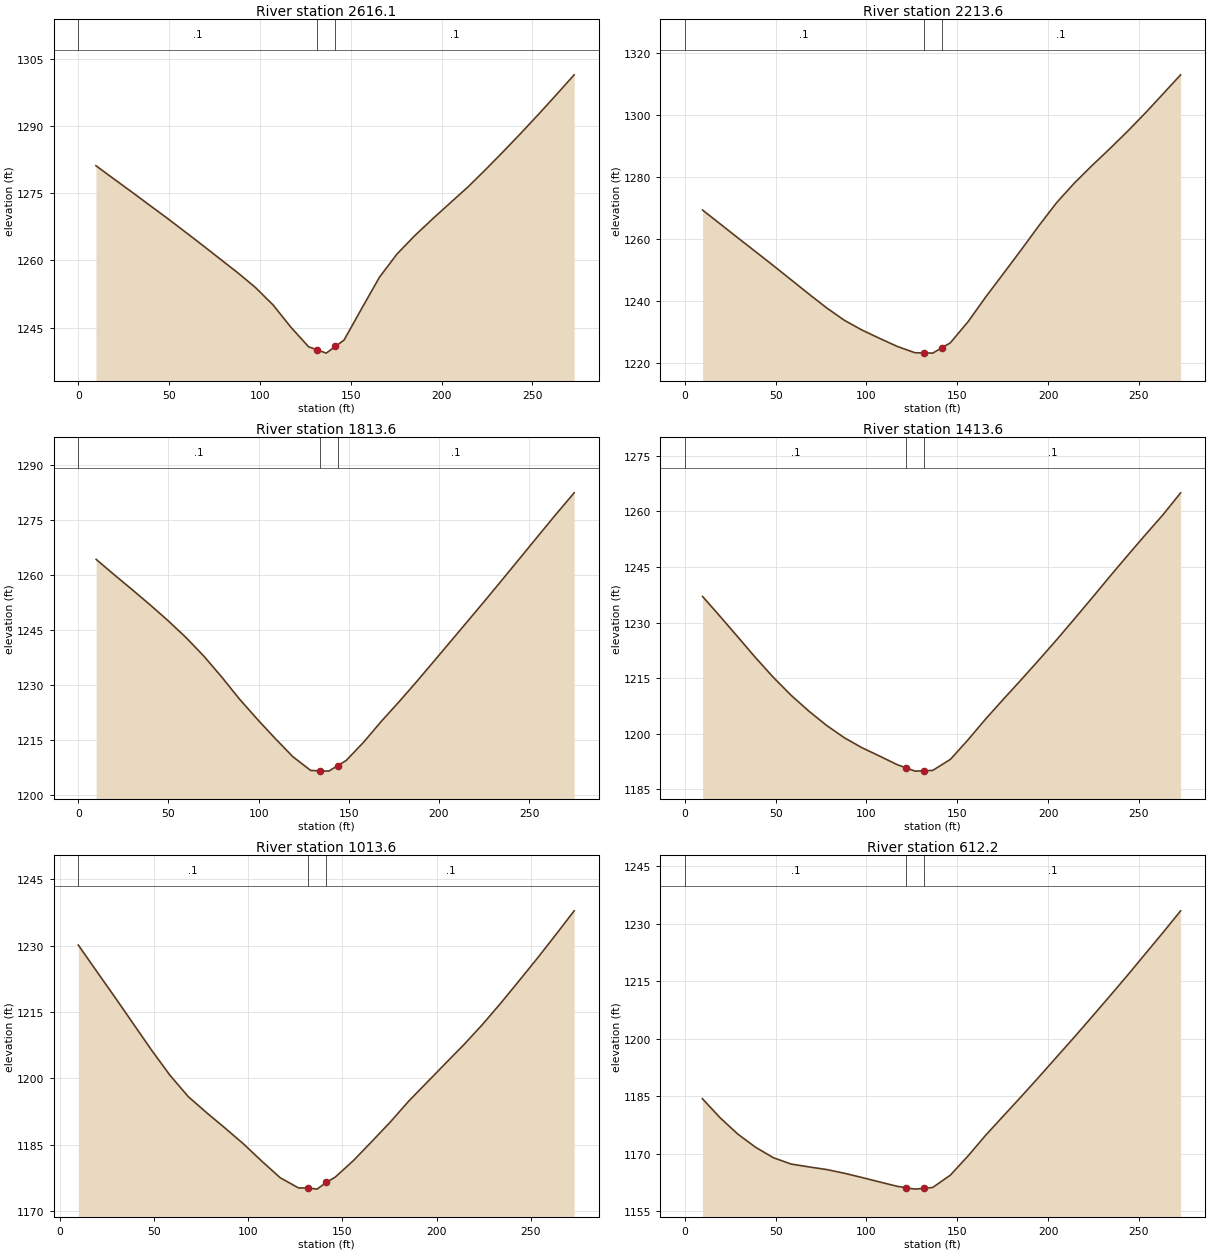
Type RM Length L Ch R = 1 ,2616.1  ,407.2,402.5,397.9
XS GIS Cut Line= 3
     1716479.001      152563.526     1716611.513      152596.282
     1716744.025      152629.038
#Sta/Elev= 30
     9.7  1281.1    19.5 1278.17    29.3 1275.28      39 1272.36    48.8 1269.43
    58.5 1266.44    68.3 1263.39      78 1260.31    87.8 1257.21    97.5 1253.94
   107.3 1250.01     117 1245.09   126.8  1240.7   131.5 1240.02   136.5 1239.29
   141.5 1240.77   146.3  1242.2     156 1249.23   165.8 1256.22   175.5 1261.42
   185.3 1265.52     195 1269.21   204.8 1272.81   214.5 1276.35   224.2 1280.22
     234 1284.26   243.8  1288.4   253.5 1292.61   263.3 1296.98     273 1301.37
#Mann= 3 , 0 , 0
       0      .1       0   131.5    .045       0   141.5      .1       0
Bank Sta=131.5,141.5
XS Rating Curve= 0 ,0
Exp/Cntr=0.3,0.1

Type RM Length L Ch R = 1 ,2213.6  ,414.1,400,382.9
XS GIS Cut Line= 3
     1716456.902      152992.803     1716593.392       152994.39
     1716729.883      152995.977
#Sta/Elev= 30
     9.8 1269.26    19.5 1264.79    29.2 1260.31      39 1255.84    48.8 1251.34
    58.5 1246.81    68.2 1242.26      78 1237.78    87.7 1233.79    97.5 1230.61
   107.2 1227.92     117 1225.31   126.7 1223.28   131.5 1223.22   136.5 1223.15
   141.5 1224.86   146.2 1226.47     156  1233.3   165.7 1241.26   175.5 1248.85
   185.2 1256.42     195 1264.24   204.7 1271.63   214.5 1277.96   224.2  1283.6
     234 1289.03   243.7  1294.6   253.5  1300.5   263.2 1306.63     273 1312.85
#Mann= 3 , 0 , 0
       0      .1       0   131.5    .045       0   141.5      .1       0
Bank Sta=131.5,141.5
XS Rating Curve= 0 ,0
Exp/Cntr=0.3,0.1

Type RM Length L Ch R = 1 ,1813.6  ,386.5,400,416.5
XS GIS Cut Line= 3
     1716490.244      153445.354     1716598.195      153358.006
     1716689.751      153257.302
#Sta/Elev= 30
     9.9 1264.29    19.8 1260.14    29.8 1256.06    39.7 1251.93    49.6 1247.64
    59.5 1243.07    69.4 1238.02    79.4 1232.27    89.3 1226.22    99.2 1220.71
   109.1 1215.47     119 1210.44   128.9 1206.69   133.9  1206.6   138.9 1206.51
   143.9 1208.02   148.6 1209.43   158.3 1214.44     168 1220.07   177.8 1225.39
   187.5 1230.85   197.2 1236.48   206.9 1242.14   216.6 1247.81   226.4 1253.56
   236.1 1259.33   245.8 1265.14   255.5 1270.97   265.2 1276.76     275 1282.45
#Mann= 3 , 0 , 0
       0      .1       0   133.9    .045       0   143.9      .1       0
Bank Sta=133.9,143.9
XS Rating Curve= 0 ,0
Exp/Cntr=0.3,0.1

Type RM Length L Ch R = 1 ,1413.6  ,408.7,400,391.4
XS GIS Cut Line= 3
     1716557.214      153741.093     1716693.696      153738.803
     1716830.166       153735.93
#Sta/Elev= 30
     9.8 1237.05    19.5 1231.64    29.3 1226.08      39 1220.52    48.8 1215.21
    58.5  1210.4    68.3 1206.12      78 1202.28    87.8 1198.94    97.5 1196.25
   107.3 1193.97     117 1191.66   121.8 1190.81   126.8 1189.92   131.8 1190.02
   136.5 1190.11   146.3 1193.12     156  1198.4   165.8 1204.07   175.5 1209.37
   185.3 1214.63     195 1219.93   204.8  1225.4   214.5 1230.99   224.3  1236.7
     234 1242.43   243.8 1248.11   253.5 1253.64   263.3 1259.11     273 1265.02
#Mann= 3 , 0 , 0
       0      .1       0   121.8    .045       0   131.8      .1       0
Bank Sta=121.8,131.8
XS Rating Curve= 0 ,0
Exp/Cntr=0.3,0.1

Type RM Length L Ch R = 1 ,1013.6  ,406.9,401.4,395.9
XS GIS Cut Line= 3
     1716700.222      154161.033     1716823.462      154102.347
     1716946.703      154043.662
#Sta/Elev= 30
     9.8 1230.12    19.5 1224.21    29.3 1218.29      39 1212.31    48.7 1206.36
    58.5 1200.66    68.2 1195.84      78 1192.19    87.7 1188.75    97.5 1185.16
   107.2 1181.27     117 1177.51   126.7 1175.22   131.5 1175.22   136.5 1174.95
   141.5 1176.48   146.2 1177.67     156 1181.48   165.7 1185.76   175.5 1190.16
   185.2 1194.85     195 1199.13   204.7 1203.37   214.5 1207.62   224.3 1212.15
     234 1216.97   243.7 1222.01   253.5 1227.16   263.2 1232.43     273 1237.86
#Mann= 3 , 0 , 0
     9.8      .1       0   131.5    .045       0   141.5      .1       0
Bank Sta=131.5,141.5
XS Rating Curve= 0 ,0
Exp/Cntr=0.3,0.1

Type RM Length L Ch R = 1 ,612.2   ,307.6,320,332.4
XS GIS Cut Line= 3
     1716962.432      154507.549     1717065.294      154417.818
     1717168.157      154328.087
#Sta/Elev= 30
     9.7 1184.39    19.5 1179.39    29.2 1175.15      39 1171.71    48.8 1168.98
    58.5 1167.34    68.2  1166.6      78 1165.91    87.7 1164.95    97.5 1163.83
   107.3 1162.66     117 1161.52   121.8 1161.16   126.8 1160.79   131.8 1161.01
   136.5 1161.22   146.2 1164.43     156 1169.48   165.7 1174.87   175.5 1179.93
   185.3 1184.97     195 1190.06   204.7 1195.25   214.5 1200.47   224.2 1205.77
     234 1211.16   243.8 1216.62   253.5 1222.16   263.3 1227.76     273 1233.42
#Mann= 3 , 0 , 0
       0      .1       0   121.8    .045       0   131.8      .1       0
Bank Sta=121.8,131.8
XS Rating Curve= 0 ,0
Exp/Cntr=0.3,0.1

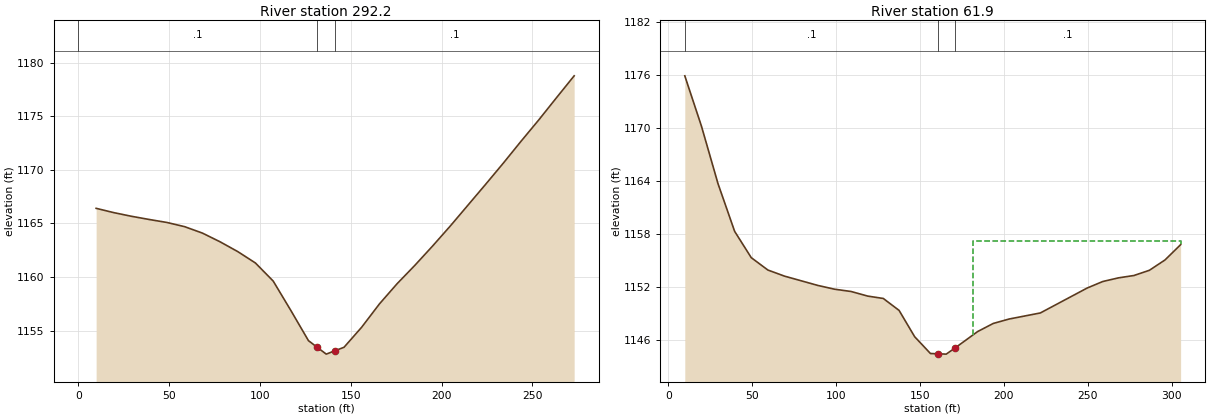
Type RM Length L Ch R = 1 ,292.2   ,238,230.3,222.6
XS GIS Cut Line= 3
     1717125.733      154673.821     1717261.531      154659.996
     1717397.318      154646.069
#Sta/Elev= 30
     9.8 1166.41    19.5 1166.01    29.2 1165.67      39 1165.37    48.8 1165.09
    58.5  1164.7    68.3  1164.1      78 1163.29    87.7 1162.38    97.5 1161.31
   107.3 1159.62     117 1156.88   126.7 1154.06   131.5 1153.44   136.5  1152.8
   141.5 1153.13   146.3 1153.44     156 1155.31   165.8 1157.49   175.5 1159.37
   185.3 1161.09     195 1162.88   204.8 1164.76   214.5  1166.7   224.2 1168.64
     234 1170.63   243.7 1172.66   253.5 1174.66   263.2 1176.72     273 1178.78
#Mann= 3 , 0 , 0
       0      .1       0   131.5    .045       0   141.5      .1       0
Bank Sta=131.5,141.5
XS Rating Curve= 0 ,0
Exp/Cntr=0.3,0.1

Type RM Length L Ch R = 1 ,61.9    ,65.5,61.9,58.3
XS GIS Cut Line= 4
     1717188.416      154830.148     1717290.656      154890.779
     1717381.986      154843.274      1717419.05      154768.329
#Sta/Elev= 29
     9.9 1175.86    19.8 1170.18    29.7 1163.65    39.6 1158.26    49.5 1155.28
    59.4 1153.88    69.3 1153.19    89.1 1152.14    99.1 1151.71     109 1151.45
   118.9 1150.93   128.2 1150.66   137.6 1149.31   146.9 1146.33   156.3 1144.43
   160.7  1144.4   165.7 1144.36   170.7 1145.02   184.4 1146.91   193.7 1147.83
   203.1 1148.33   221.8 1149.02   249.7 1151.84     259 1152.58   268.3 1152.99
   277.6 1153.26   286.8 1153.85   296.1 1155.02   305.4 1156.75
#Mann= 3 , 0 , 0
     9.9      .1       0   160.7    .045       0   170.7      .1       0
#XS Ineff= 2 , 0
                          181.46         1157.12
Permanent Ineff=
       F       F
Bank Sta=160.7,170.7
XS Rating Curve= 0 ,0
Exp/Cntr=0.3,0.1
Stream Node=Hurricane Bra...,Main            , 0 , 0 ,Upstream end
Stream Node=Hurricane Bra...,Main            , 0 , 1 ,Downstream end

Chan Stop Cuts=-1
Use User Specified Reach Order=0